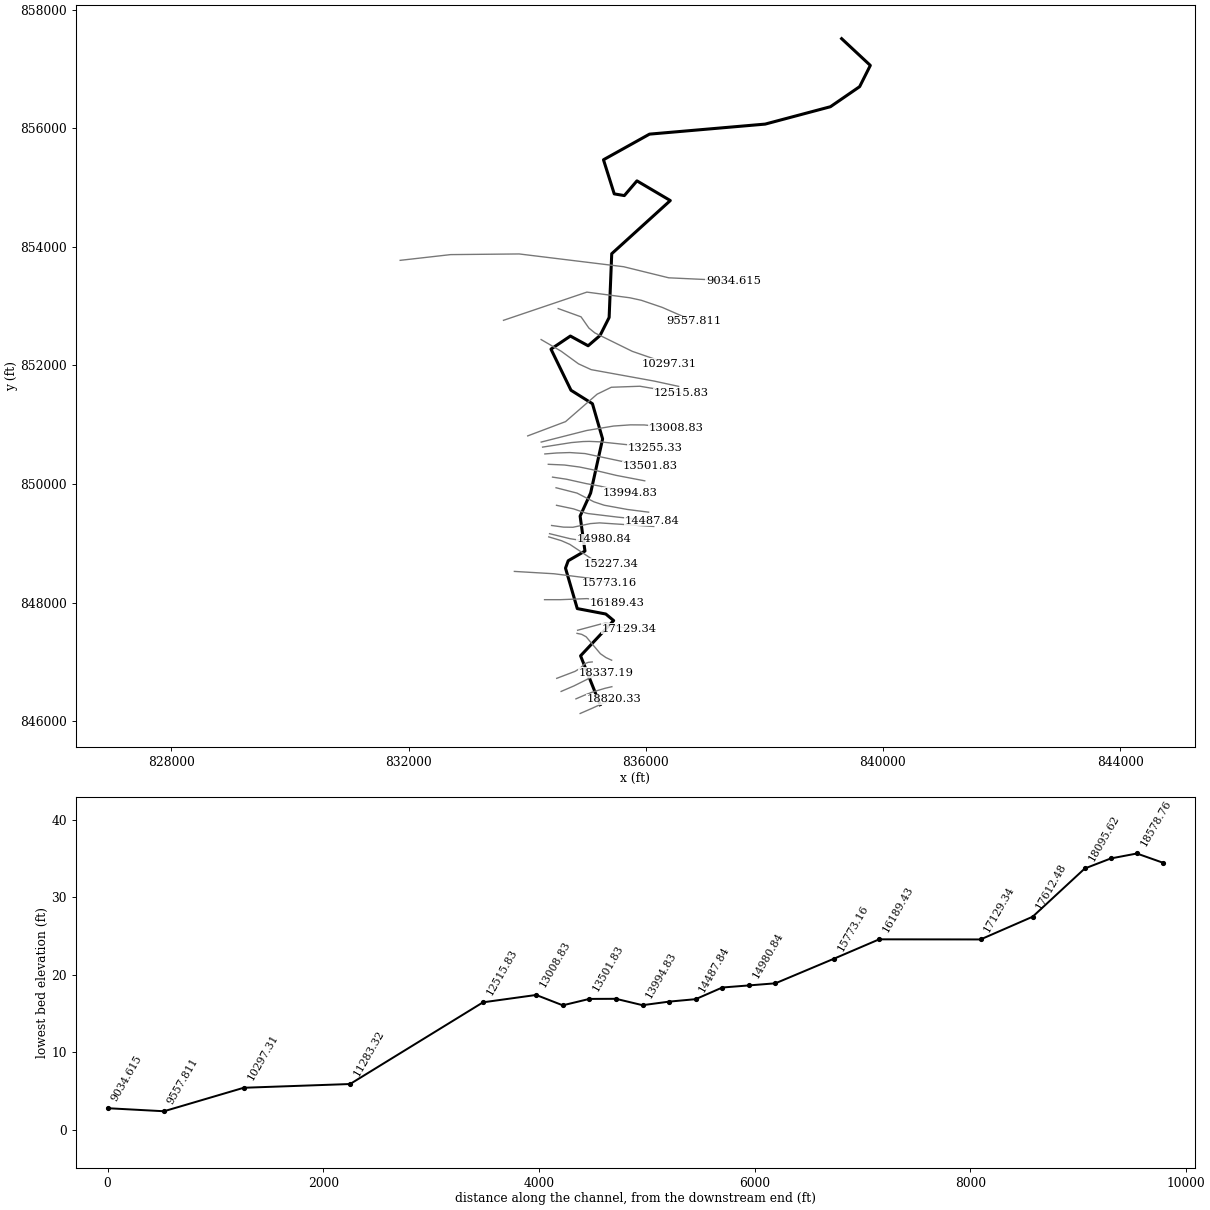
--- 18446_ras.prj (project) ---

Proj Title=18446
Current Plan=p01
Default Exp/Contr=0.3,0.1
English Units
Geom File=g01
Flow File=f01
Plan File=p01
Y Axis Title=Elevation
X Axis Title(PF)=Main Channel Distance
X Axis Title(XS)=Station
BEGIN DESCRIPTION:
RFD model 18446 exported to HEC-RAS
END DESCRIPTION:

--- 18446_ras.p01 (plan) ---

Plan Title=Plan 01
Program Version=4.10
Short Identifier=Plan 01
Geom File=g01
Flow File=f01
Subcritical Flow
Calc Critical at every XS
Secant Critical Depth

--- 18446_ras.f01 (steady flow) ---

Flow Title=Flow 01
Program Version=5.01
Number of Profiles= 6
Profile Names=10yr,25yr,50yr,100yr,100plus,500yr
River Rch & RM=18446,32,18820.33
11883.5817952.78 23430.727906.92 40744.136174.87
River Rch & RM=18446,32,18578.76
11886.5517957.6823437.4627915.3540756.4136185.36
River Rch & RM=18446,32,18337.19
11889.0217961.7523443.0527922.3240766.59   36194
River Rch & RM=18446,32,18095.62
11910.4417996.8723491.2927982.3140854.1736268.04
River Rch & RM=18446,32,17612.48
11916.2818006.57 23504.727999.0840878.6636289.01
River Rch & RM=18446,32,17129.34
12052.6218232.8623817.6228390.5141450.15 36777.9
River Rch & RM=18446,32,16189.43
12108.33 18324.823944.3628548.63   4168136973.96
River Rch & RM=18446,32,15773.16
12111.9618330.8923952.8428559.2941696.5736987.43
River Rch & RM=18446,32,15227.34
12137.3218373.3124011.7628633.2841804.5937080.41
River Rch & RM=18446,32,14980.84
12142.5718382.1424024.0628648.76 41827.237099.97
River Rch & RM=18446,32,14734.34
12144.7118385.7324029.0728655.0641836.3937107.91
River Rch & RM=18446,32,14487.84
12155.5818403.9924054.4928687.0341883.0737148.25
River Rch & RM=18446,32,14241.33
12243.9118552.52 24261.428947.47 42263.337476.97
River Rch & RM=18446,32,13994.83
12246.7918557.3924268.2228956.0842275.8837487.93
River Rch & RM=18446,32,13748.33
12250.1518563.0824276.1828966.1442290.5737500.71
River Rch & RM=18446,32,13501.83
12262.6118584.2124305.7429003.4842345.0837548.18
River Rch & RM=18446,32,13255.33
12267.2418592.0624316.7329017.3642365.3537565.82
River Rch & RM=18446,32,13008.83
12272.3518600.7224328.8529032.67 42387.737585.28
River Rch & RM=18446,32,12515.83
12289.7418630.28 24370.329085.1242464.2737652.16
River Rch & RM=18446,32,11283.32
12829.0719518.7725594.2730611.5644692.8839530.61
River Rch & RM=18446,32,10297.31
12924.8719681.5325822.4530900.3145114.4539896.02
River Rch & RM=18446,32,9557.811
12950.8619725.8925884.7830979.3345229.8339996.37
River Rch & RM=18446,32,9034.615
12971.8319761.7225935.1731043.2745323.1740077.64
River Rch & RM=18446,32,8816.608
12972.7519763.2925937.3831046.0745327.26 40081.2
River Rch & RM=18446,32,8325.039
12976.2619769.2925945.8231056.7945342.9140094.84
River Rch & RM=18446,32,7611.385
13029.5619860.2226073.5931218.7945579.4340300.36
River Rch & RM=18446,32,6080.502
13053.0119900.3226130.0231290.4345684.0340391.45
River Rch & RM=18446,32,5232.538
13107.4219993.4126261.0331456.7645926.8740602.88
River Rch & RM=18446,32,4994.654
13110.46 19998.626268.3431466.0445940.4340614.67
Boundary for River Rch & Prof#=18446,32,1
Up Type= 0
Dn Type= 2
Boundary for River Rch & Prof#=18446,32,2
Up Type= 0
Dn Type= 2
Boundary for River Rch & Prof#=18446,32,2
Up Type= 0
Dn Type= 2
Boundary for River Rch & Prof#=18446,32,2
Up Type= 0
Dn Type= 2
Boundary for River Rch & Prof#=18446,32,2
Up Type= 0
Dn Type= 2
Boundary for River Rch & Prof#=18446,32,2
Up Type= 0
Dn Type= 2

--- 18446_ras.g01 (geometry) ---

Geom Title=18446
Program Version=4.10

River Reach=18446,32
Reach XY= 30
835230.200907499 846279.25322527834901.327246787 847103.06846165
835458.929197072847697.606343604 835326.50964123847807.973073504
834845.793831259847899.464048005834647.219490143848581.387762413
 834692.91190261848706.603132975 834975.21028197848869.618359103
834893.664138527849458.945339073835070.876138898849848.020763151
835272.892801761850760.357127602835101.433736297851354.545395711
834739.668562922851581.326510569834402.024787846852274.887744851
834729.431584838852495.567355301835028.622690025 852331.66398581
835229.518743278852504.410706643835382.979169189852808.581297075
835426.698292108853884.064699662 836414.41457659 854780.45237329
835851.914576619855112.483623315835639.227126452854864.178155394
835469.161116901 854893.05712246835287.543843004855468.445831975
836063.672130439855900.559443805838014.626991572856069.830277167
839114.887408257856362.799027135839607.508936047856701.340693794
 839787.63046378857059.413610457839303.689491573857510.802499363

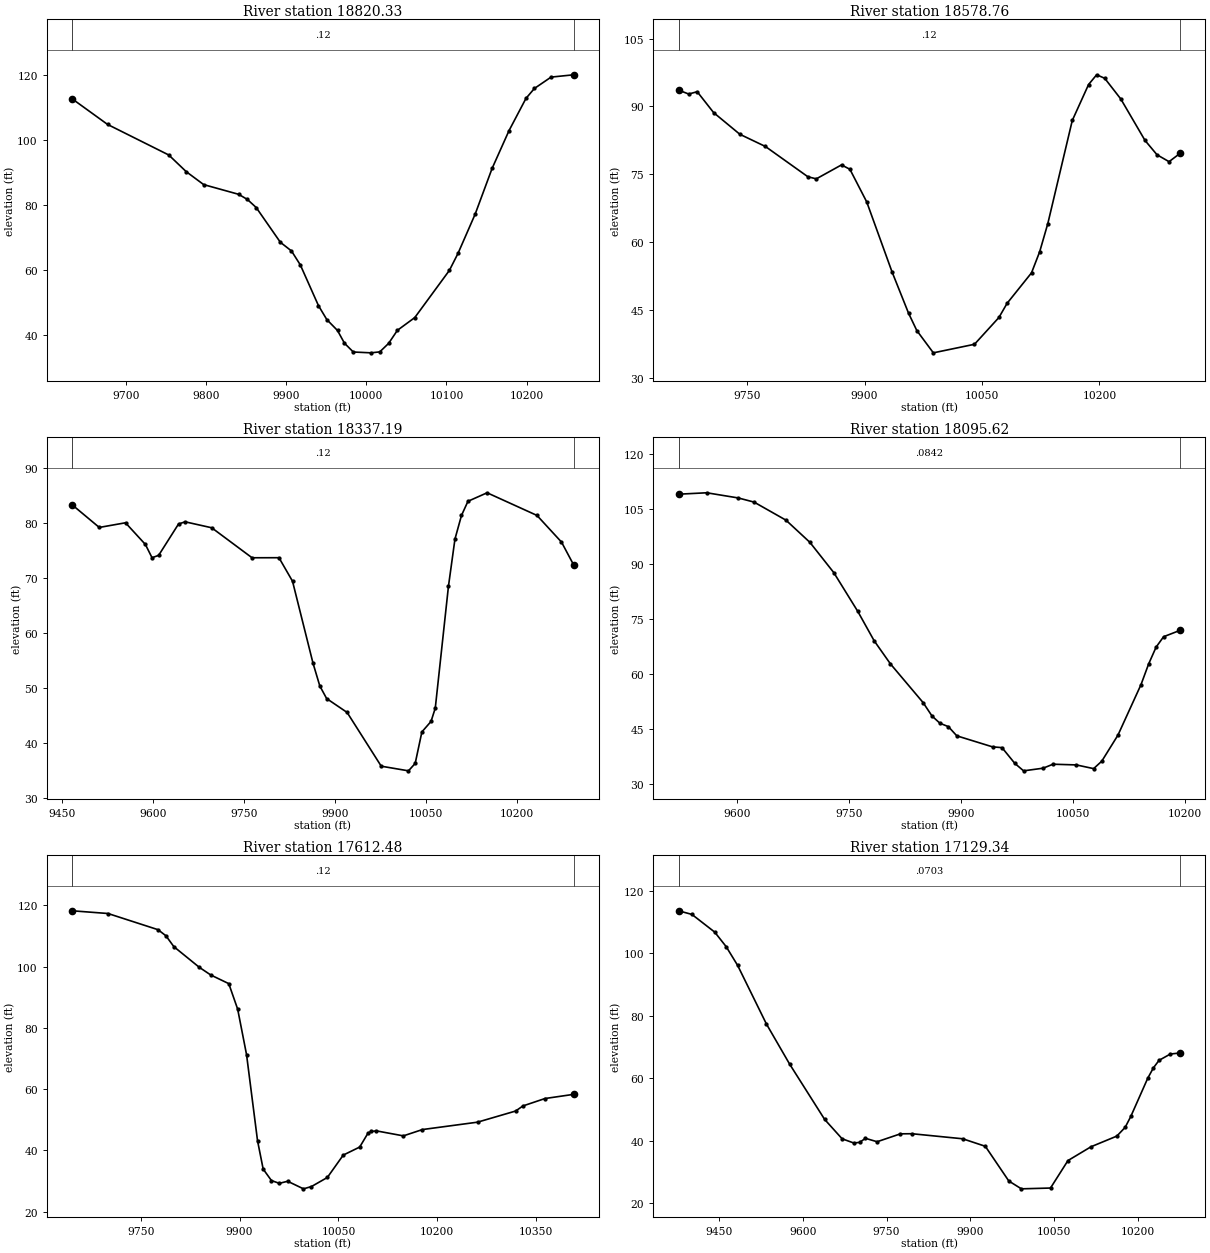
Type RM Length L Ch R = 1 ,18820.33,241.569400,241.569400,241.569400
XS GIS Cut Line= 6
834894.293187175846130.466218622 835102.04043997846220.929961656
835271.178616837846299.193369713835347.737482669846330.197748341
835421.183776427846355.377617323835472.286858741846370.359356648
#Sta/Elev= 30
9632.619112.79939676.951104.88429753.32895.46112 9775.1590.315829796.97286.31982
9840.61683.328929851.527 81.73839862.47179.263159892.66468.53625 9906.5665.85574
9917.58261.556689940.21849.004379950.649 44.69779963.99541.332689972.69437.40517
9983.71634.6966110005.7634.4385910016.7734.7362910027.7737.3434410038.7841.38395
10060.4945.3208510103.6459.8572710114.4365.1037410135.8577.21886   1015791.32184
10178.14102.982510199.28112.9121 10209.8115.975410230.64 119.48310259.07 120.199
#Mann= 3 , 0 , 0
9632.619    0.12       09632.619    0.12       010259.07    0.12       0
#XS Ineff= 2 , 0
       0                               0
Bank Sta=9632.619,10259.07
Exp/Cntr=0.3,0.1

Type RM Length L Ch R = 1 ,18578.76,241.569400,241.569400,241.569400
XS GIS Cut Line= 6
834823.081075195846377.224467134 834963.18887687846437.726570589
835079.403564585846483.205936016835135.556488934 846502.37312889
835315.963455359846555.961968952835429.146156376 846582.28892749
#Sta/Elev= 30
9662.25693.620749675.23992.750489686.13293.259199707.09488.648369740.59483.86746
9773.27281.172539827.55374.487249838.29174.028799870.50677.108289881.24576.13696
9902.72268.936969934.93753.551669956.14644.382339966.71240.548439987.84535.62652
10040.4137.5146710071.6643.4317410082.0746.5520610113.3153.2882810123.7357.94201
10134.1464.1701610165.3886.9135410186.21 94.850610196.5296.9996110206.8196.22578
10227.4191.64927 10258.382.5131710273.6379.3473410289.0377.8198910303.4479.70021
#Mann= 3 , 0 , 0
9662.256    0.12       09662.256    0.12       010303.44    0.12       0
#XS Ineff= 2 , 0
       0                               0
Bank Sta=9662.256,10303.44
Exp/Cntr=0.3,0.1

Type RM Length L Ch R = 1 ,18337.19,241.569400,241.569400,241.569400
XS GIS Cut Line= 6
834573.413745315846502.510519576834788.014275697846594.787408151
835121.498254792846761.011406468835198.578924464846789.164095526
835247.882072367846801.931547531835335.249407659846815.047065198
#Sta/Elev= 30
9466.49583.381389511.36779.253579554.63280.101159587.44676.158269598.38373.74695
9609.32174.180379642.13479.885879653.07280.274389696.82379.194329763.37173.73844
9807.76973.74939 9830.1169.475369863.88754.582279875.14650.424029886.40548.13235
9920.18245.607929976.47735.8321810021.4334.9885810032.4836.3436410043.5242.06507
10058.6243.9773310065.6146.3989210087.3168.5212910098.0677.1364110108.8181.42696
10119.5184.0095210151.1185.5571610233.3981.4358510273.8176.59191 10294.272.36729
#Mann= 3 , 0 , 0
9466.495    0.12       09466.495    0.12       0 10294.2    0.12       0
#XS Ineff= 2 , 0
       0                               0
Bank Sta=9466.495,10294.2
Exp/Cntr=0.3,0.1

Type RM Length L Ch R = 1 ,18095.62,483.138800,483.138800,483.138800
XS GIS Cut Line= 6
834499.200038128846723.118388943834808.078988457846840.991610186
 834893.23356277846892.869935104834974.798244574846971.421361948
835032.499886492846993.365698088835097.363535097847000.002773553
#Sta/Elev= 30
9521.473108.99419559.254109.37899601.466107.97059622.604106.84229665.283 101.928
9697.29395.901469729.30287.660899761.51877.079069783.36969.105269805.21962.79638
 9848.9252.273499860.84848.622699871.43246.649679882.74845.725779894.06443.22082
9941.93640.21546 9954.5740.011539971.74435.719799983.46233.6927410009.6134.41336
10022.8735.4966810054.15 35.303210077.2634.2957710088.1736.32386 10109.843.40117
 10140.757.1640510150.87 62.764410160.9467.3786810170.9570.2009110193.3471.95835
#Mann= 3 , 0 , 0
9521.473  0.0842       09521.473  0.0842       010193.34  0.0842       0
#XS Ineff= 2 , 0
       0                               0
Bank Sta=9521.473,10193.34
Exp/Cntr=0.3,0.1

Type RM Length L Ch R = 1 ,17612.48,483.138800,483.138800,483.138800
XS GIS Cut Line= 6
834841.267275955847481.750325799 834920.12740111847465.263274741
834995.501468931 847423.67263488835235.485526076847138.377604656
835328.783110419847073.758331862835425.345782737847028.711083469
#Sta/Elev= 30
 9645.67118.2038 9700.19117.31429776.119112.0365 9788.16110.0488  9800.2106.4963
9838.80999.759439856.26697.247829883.579 94.43029897.08186.102479910.58271.24186
9927.23343.178629935.79833.921029948.351 30.18419960.31929.271359972.96429.95232
9996.97427.4769810009.0428.2189810033.2131.1832410057.3938.4917410082.3441.10952
10095.0445.6796310099.88 46.197310107.8446.3842810148.6344.7591110177.5946.81993
10261.2449.2299710318.9952.8598910330.18 54.528110363.7356.9494610407.4758.31551
#Mann= 3 , 0 , 0
 9645.67    0.12       0 9645.67    0.12       010407.47    0.12       0
#XS Ineff= 2 , 0
       0                               0
Bank Sta=9645.67,10407.47
Exp/Cntr=0.3,0.1

Type RM Length L Ch R = 1 ,17129.34,939.917100,939.917100,939.917100
XS GIS Cut Line= 6
834851.428873672847534.276175158835234.020910163847636.671515115
835317.856206269847652.315560277835385.405126017847646.081119753
835554.937415507847590.651379208835722.649453525847561.670875479
#Sta/Elev= 30
9377.426113.5851  9401.4112.41969442.213106.75419462.714102.10449483.21596.10817
9534.814 77.33069576.35464.486839639.02646.785529670.36240.569429691.25339.22377
9701.69839.423719712.14440.723679733.03439.62861  9774.842.157739795.36942.19421
9886.31740.57475 9926.8138.169959968.89427.052369991.41424.5453110043.5424.80315
10074.7833.5967810116.0538.0171510162.2241.4268910177.2244.2306510187.3447.72841
10217.6959.9689610227.8163.2900210237.93 65.694410258.1667.7140510276.0268.06372
#Mann= 3 , 0 , 0
9377.426  0.0703       09377.426  0.0703       010276.02  0.0703       0
#XS Ineff= 2 , 0
       0                               0
Bank Sta=9377.426,10276.02
Exp/Cntr=0.3,0.1

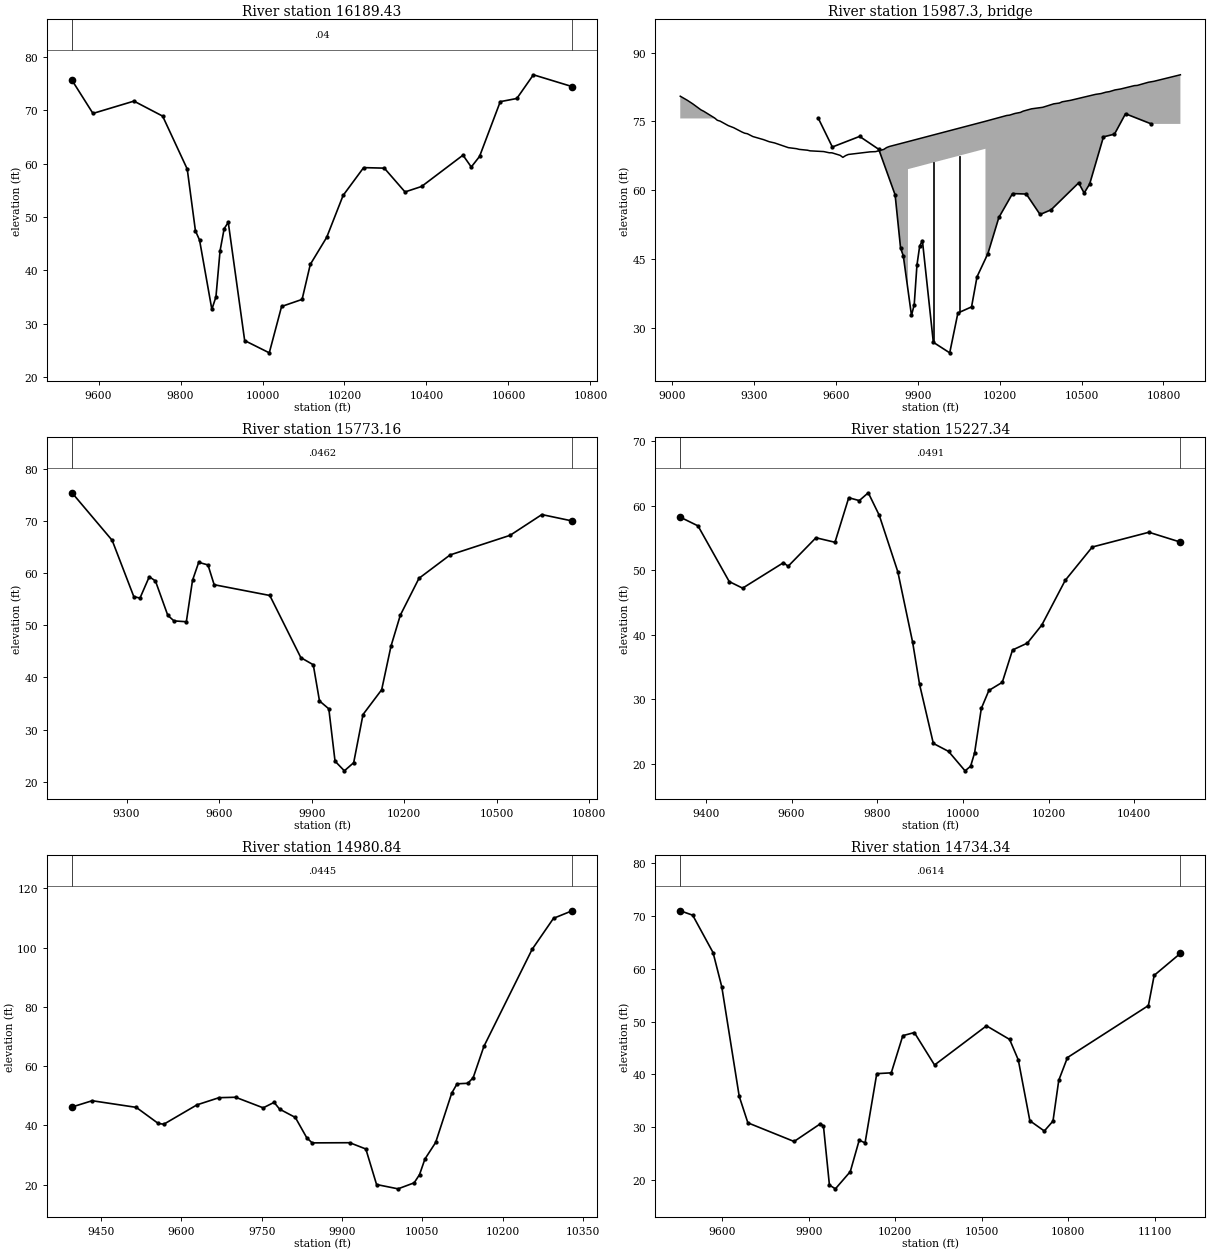
Type RM Length L Ch R = 1 ,16189.43,416.265800,416.265800,416.265800
XS GIS Cut Line= 4
834293.826757729848049.867636099834562.582626104848049.867636099
835010.509073347848067.784693986 835508.60328266847996.116462439
#Sta/Elev= 30
9535.14775.64754 9586.32 69.4278 9686.32 71.7352 9756.3268.92577 9816.3359.00033
9836.34647.416829846.35445.704239876.37832.713519886.38635.057039896.39443.68232
9906.40247.82818 9916.4149.017029956.44226.8589610016.4924.5602710046.5133.24991
10096.5534.5745810116.5741.13642 10156.646.2111110196.6354.0609410246.6759.27224
10297.1459.1742810347.6554.7149910388.0655.7372910489.0961.60711 10509.359.38716
10529.5161.3698210580.0271.6349210620.4372.2289210660.8476.6721810755.4174.45721
#Mann= 3 , 0 , 0
9535.147    0.04       09535.147    0.04       010755.41    0.04       0
#XS Ineff= 2 , 0
       09748.989                       0
Bank Sta=9535.147,10755.41
Exp/Cntr=0.3,0.1

Type RM Length L Ch R = 3 , 15987.3,,,
BEGIN DESCRIPTION:
END DESCRIPTION:
Bridge Culvert--1,0,-1,-1, 0
Deck Dist Width WeirC Skew NumUp NumDn MinLoCord MaxHiCord MaxSubmerge Is_Ogee
154.632900,107.000000,2.6,0, 60, 60, , , 0.95, 0, 0,0,,
 9028.80 9054.76 9074.76 9104.76 9114.77 9154.77 9164.78 9174.78 9204.78 9224.79
 9254.79 9264.79 9274.79 9294.80 9334.80 9354.81 9374.81 9424.82 9454.83 9464.83
 9494.83 9504.83 9554.84 9574.85 9584.85 9614.85 9624.86 9634.86 9644.86 9724.87
 9744.88 9774.92 9784.94 9794.65 9863.51 9863.5110147.5110147.5110225.5510235.56
10255.5910275.6610285.8610316.4410357.2210398.0110418.4010428.5910459.1810550.94
10571.3310588.9710601.9110622.3010642.6910693.6710703.8710744.6510765.0410862.07
   80.50   79.61   78.83   77.52   77.22   75.75   75.25   75.07   74.09   73.63
   72.70   72.44   72.32   71.71   71.02   70.58   70.31   69.29   69.06   68.91
   68.73   68.59   68.43   68.17   68.16   67.61   67.17   67.55   67.80   68.37
   68.42   68.91   69.30   69.53   70.60   70.60   75.04   75.04   76.30   76.37
   76.74   76.97   77.25   77.75   78.08   78.84   79.01   79.28   79.60   80.90
   81.08   81.38   81.50   81.87   82.07   82.81   82.85   83.54   83.75   85.17
 -919.50 -920.39 -921.17 -922.48 -922.78 -924.25 -924.75 -924.93 -925.91 -926.37
 -927.30 -927.56 -927.68 -928.29 -928.98 -929.42 -929.69 -930.71 -930.94 -931.09
 -931.27 -931.41 -931.57 -931.83 -931.84 -932.39 -932.83 -932.45 -932.20 -931.63
 -931.58 -931.09 -930.70 -930.47 -929.40   64.60   69.04 -924.96 -923.70 -923.63
 -923.26 -923.03 -922.75 -922.25 -921.92 -921.16 -920.99 -920.72 -920.40 -919.10
 -918.92 -918.62 -918.50 -918.13 -917.93 -917.19 -917.15 -916.46 -916.25 -914.83
 9028.80 9054.76 9074.76 9104.76 9114.77 9154.77 9164.78 9174.78 9204.78 9224.79
 9254.79 9264.79 9274.79 9294.80 9334.80 9354.81 9374.81 9424.82 9454.83 9464.83
 9494.83 9504.83 9554.84 9574.85 9584.85 9614.85 9624.86 9634.86 9644.86 9724.87
 9744.88 9774.92 9784.94 9794.65 9876.45 9876.4510160.4510160.4510225.5510235.56
10255.5910275.6610285.8610316.4410357.2210398.0110418.4010428.5910459.1810550.94
10571.3310588.9710601.9110622.3010642.6910693.6710703.8710744.6510765.0410862.07
   80.50   79.61   78.83   77.52   77.22   75.75   75.25   75.07   74.09   73.63
   72.70   72.44   72.32   71.71   71.02   70.58   70.31   69.29   69.06   68.91
   68.73   68.59   68.43   68.17   68.16   67.61   67.17   67.55   67.80   68.37
   68.42   68.91   69.30   69.53   70.80   70.80   75.25   75.25   76.30   76.37
   76.74   76.97   77.25   77.75   78.08   78.84   79.01   79.28   79.60   80.90
   81.08   81.38   81.50   81.87   82.07   82.81   82.85   83.54   83.75   85.17
 -919.50 -920.39 -921.17 -922.48 -922.78 -924.25 -924.75 -924.93 -925.91 -926.37
 -927.30 -927.56 -927.68 -928.29 -928.98 -929.42 -929.69 -930.71 -930.94 -931.09
 -931.27 -931.41 -931.57 -931.83 -931.84 -932.39 -932.83 -932.45 -932.20 -931.63
 -931.58 -931.09 -930.70 -930.47 -929.20   64.80   69.25 -924.75 -923.70 -923.63
 -923.26 -923.03 -922.75 -922.25 -921.92 -921.16 -920.99 -920.72 -920.40 -919.10
 -918.92 -918.62 -918.50 -918.13 -917.93 -917.19 -917.15 -916.46 -916.25 -914.83
Pier Skew, UpSta & Num, DnSta & Num=  ,9957.51, 2 ,9970.45, 2 , 0 , 0 , 0 ,,
    4.00    4.00
 -927.93   72.07
    4.00    4.00
 -927.73   72.27
Pier Skew, UpSta & Num, DnSta & Num=  ,10053.51, 2 ,10066.45, 2 , 0 , 0 , 0 ,,
    4.00    4.00
 -926.43   73.57
    4.00    4.00
 -926.22   73.78
BR Coef=-1 , 0 , 0 ,, 0 ,,,0.8,0,1,0,
WSPro=,,,, 1 ,,,, 0 ,,,, 0 ,,,,-1 ,-1 ,-1 , 0 , 0 , 0 , 0 , 0
BC Design=,, 0 ,, 0 ,,,,,,

Type RM Length L Ch R = 1 ,15773.16,545.821700,545.821700,545.821700
XS GIS Cut Line= 4
833784.982313693848526.461375967 834451.49686715848487.043848634
835053.510012299848411.792205468835390.350700647848329.373739198
#Sta/Elev= 30
 9123.1375.416429253.37566.292119323.49755.497589343.53255.214769373.58559.31151
 9393.6258.50254 9433.6951.897559453.72550.842249493.79450.678789513.82958.62853
9533.86462.072779563.917 61.57389583.95257.781469764.26655.717739864.88543.79516
9905.19642.427169925.35135.487789955.58533.973589975.74123.9384710005.9722.08022
10036.2123.6451810066.4432.8851710126.9137.6349510157.1446.0039810187.3751.94156
10247.8459.0101510348.6263.4915210543.1767.2558110646.1271.2359510744.2870.01357
#Mann= 3 , 0 , 0
 9123.13  0.0462       0 9123.13  0.0462       010744.28  0.0462       0
#XS Ineff= 2 , 0
       0                               0
Bank Sta=9123.13,10744.28
Exp/Cntr=0.3,0.1

Type RM Length L Ch R = 1 ,15227.34,246.501300,246.501300,246.501300
XS GIS Cut Line= 6
 834364.77826617849108.675044944834578.192564166849044.841538768
834720.539996836848982.272761081835133.662877283848707.973109503
835292.802146115848662.837272274835418.257360337848651.765041902
#Sta/Elev= 30
9340.10858.247599381.54756.897059454.45448.253129485.72147.236119581.10651.19049
9591.89450.626969656.89155.054079701.29754.352749733.41361.266569758.06160.82005
9779.03962.032789804.74858.524959847.96149.786399882.617 38.83039898.74932.30976
9930.90223.144779966.50321.9040210004.9918.8900310017.8919.6002410027.23 21.6755
10042.8928.5640710060.5631.3605910091.8432.6243410115.7437.63582 10150.438.70792
10184.1241.5087810238.7448.4402110301.9453.6175610434.1955.9070910507.6754.37791
#Mann= 3 , 0 , 0
9340.108  0.0491       09340.108  0.0491       010507.67  0.0491       0
#XS Ineff= 2 , 0
       0                               0
Bank Sta=9340.108,10507.67
Exp/Cntr=0.3,0.1

Type RM Length L Ch R = 1 ,14980.84,246.501200,246.501200,246.501200
XS GIS Cut Line= 6
 834378.23388162849163.015030405834723.373984417849078.453007521
834842.396027933849059.229111267834920.490790249849057.815867325
 835132.25095079849070.650246143835299.781961781849069.673731996
#Sta/Elev= 30
9395.82146.214469433.50148.331319515.75346.09382 9556.9940.654579567.29940.41213
9629.15446.93895 9670.3949.358669701.318 49.50099752.84545.931869773.232 47.7805
9783.42645.500169812.81842.698139834.147 35.84379844.22434.114479914.47834.17151
 9944.4832.055579964.51420.0728510004.62 18.617610034.7120.6470510044.7423.40855
10054.77 28.660410074.8234.2473310104.8550.8877110114.8654.0369110134.8754.21071
10144.8856.08487 10164.966.64842 10254.9 99.3602 10294.9109.8461 10329.7112.3842
#Mann= 3 , 0 , 0
9395.821  0.0445       09395.821  0.0445       0 10329.7  0.0445       0
#XS Ineff= 2 , 0
       0                               0
Bank Sta=9395.821,10329.7
Exp/Cntr=0.3,0.1

Type RM Length L Ch R = 1 ,14734.34,246.501300,246.501300,246.501300
XS GIS Cut Line= 6
834412.413610469849301.048550734834613.872066393849273.247462576
834772.065761088 849270.98817835835065.597308316849332.711912234
835222.003307808 849344.72947378836135.765258161849284.407558113
#Sta/Elev= 30
9454.49970.994139497.63170.158019568.39763.068389598.68156.568189659.03735.87139
9689.08430.84528 9849.4427.312659940.92730.682439951.27730.247129971.97719.06379
9992.67718.3466510044.3321.6026910075.2727.5585710095.6427.04818 10136.240.15598
 10186.540.3105710226.5847.34984 10266.647.9367110336.62 41.793410516.8449.21031
10597.0646.6358210627.1542.7637110667.2731.2392410717.4229.2977510747.5131.17414
10767.5738.8997910797.6643.19975 11078.5 53.046711098.5558.7650111189.5462.93044
#Mann= 3 , 0 , 0
9454.499  0.0614       09454.499  0.0614       011189.54  0.0614       0
#XS Ineff= 2 , 0
       09793.684        10248.48       0
Bank Sta=9454.499,11189.54
Exp/Cntr=0.3,0.1

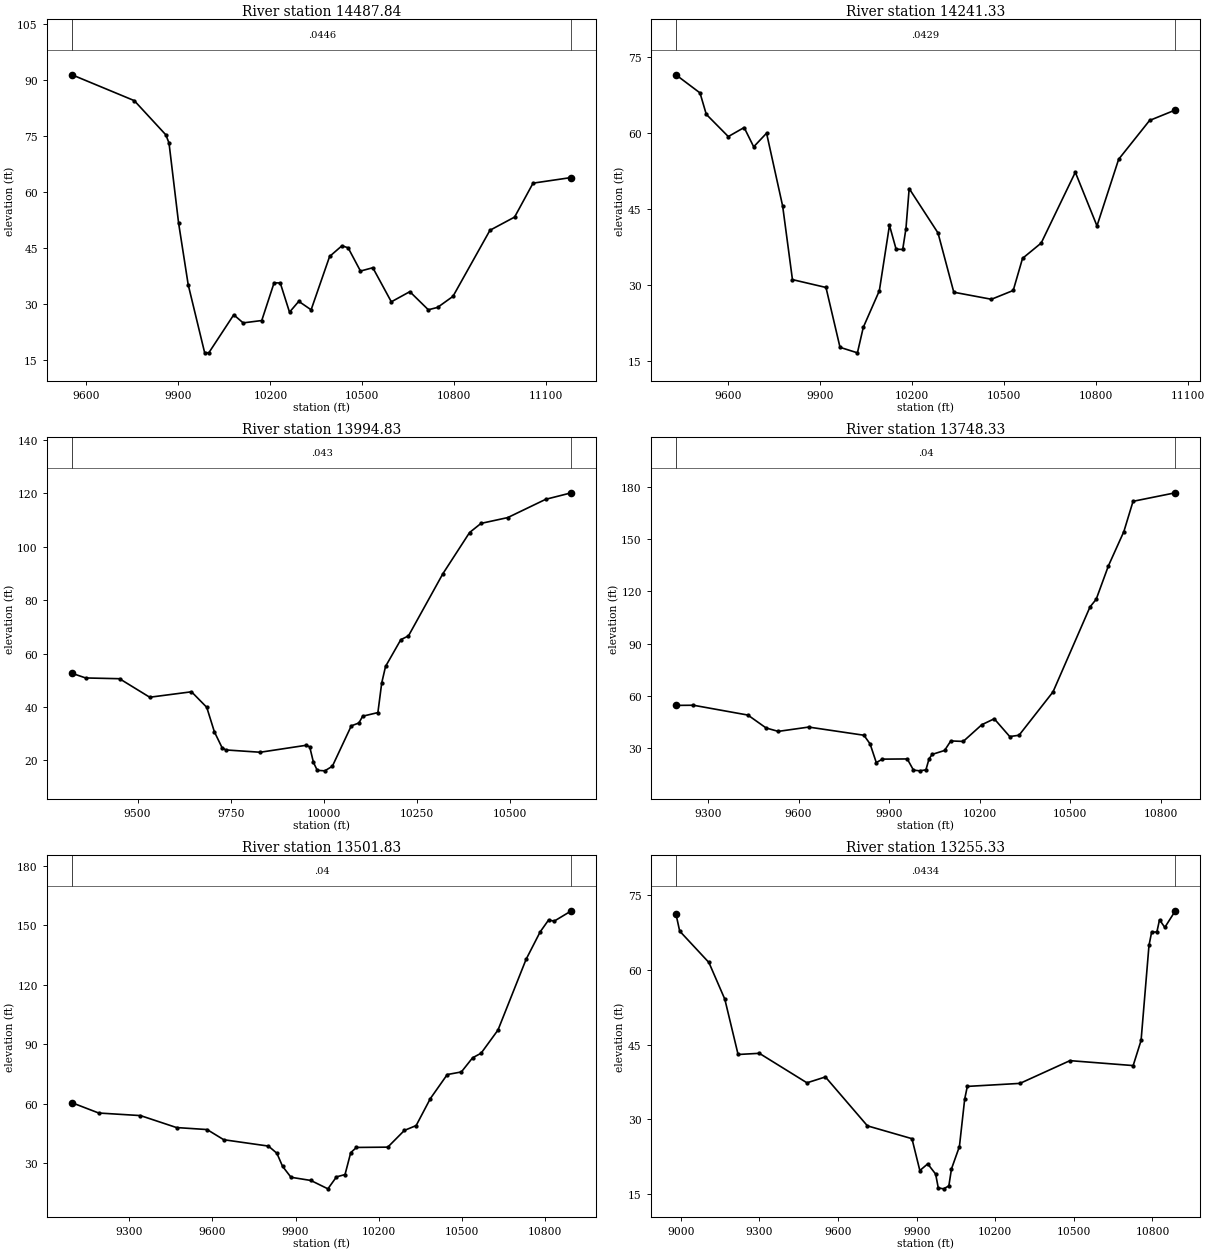
Type RM Length L Ch R = 1 ,14487.84,246.501200,246.501200,246.501200
XS GIS Cut Line= 6
 834495.60270758849641.412420284834782.358399974849581.180700557
834985.397202835 849511.90428009835029.998397735849501.652974161
835524.752088414849442.225691237836099.650553346849384.152933313
#Sta/Elev= 30
9552.54691.394399755.86684.464539858.80175.297979869.224 73.11449900.49351.64805
9931.82235.113349985.35116.93373    999916.8456610080.4427.0443310111.1524.87606
10171.8325.5081910212.0935.6216810232.2235.5785810262.4227.7461210292.6230.65485
10332.8928.3802810393.2942.6924610433.5545.5563610453.6944.9992910493.9538.77279
10534.2239.6639210594.6230.5239610654.9733.2477310715.3128.3930110745.4829.02379
10795.76  31.98610916.4449.7079110996.8153.2438211057.0762.3413111182.2763.85162
#Mann= 3 , 0 , 0
9552.546  0.0446       09552.546  0.0446       011182.27  0.0446       0
#XS Ineff= 2 , 0
       0                10273.45       0
Bank Sta=9552.546,11182.27
Exp/Cntr=0.3,0.1

Type RM Length L Ch R = 1 ,14241.33,246.501300,246.501300,246.501300
XS GIS Cut Line= 6
834487.910901802849937.471556875834841.494304932849847.096342534
835125.863963886849700.177305025835300.629792607 849642.42841174
835691.242958585849570.987551563836048.416721056849525.655898681
#Sta/Elev= 30
9430.36571.578079508.99367.984619529.42463.752819601.20459.345619652.849 61.1357
9683.94357.317129725.92160.015919778.39345.569369810.25731.024829919.52529.47122
9965.29317.61852   1002216.5279810041.1421.5791310093.4428.8195110126.4641.77793
10148.0237.0621210169.5736.9882610180.14 41.115210190.6849.0493210284.6540.26005
 10336.128.5283510458.7227.1334310529.7428.8748810560.1235.2315210620.88  38.261
10732.1452.2843910802.7341.6605710873.3254.8468310974.1662.5350411058.1564.60691
#Mann= 3 , 0 , 0
9430.365  0.0429       09430.365  0.0429       011058.15  0.0429       0
#XS Ineff= 2 , 0
       0                10219.91       0
Bank Sta=9430.365,11058.15
Exp/Cntr=0.3,0.1

Type RM Length L Ch R = 1 ,13994.83,246.501200,246.501200,246.501200
XS GIS Cut Line= 6
  834428.5191169850116.560631366 834662.71170628850081.317901185
834997.322673773850006.943613347835218.060958911849967.204371326
835473.595548884849908.909760294   835742.905613849854.011562361
#Sta/Elev= 30
9323.77752.604939360.54250.853369451.437 50.57159532.55743.632919644.70845.67402
9685.63639.864449706.15330.67983 9726.6724.777759736.92923.896359829.256 23.0326
9951.87125.626869962.02825.078569972.18419.19803 9982.3416.2664510002.6516.06978
10022.92 17.797610073.6832.9099610094.0633.9916710104.2536.5261210145.1237.88543
10155.3848.9709810165.6455.1607710206.6765.1944710227.1866.6050110319.4989.86422
10391.29105.318410421.97108.732510493.58110.901610595.54117.747610664.71120.1984
#Mann= 3 , 0 , 0
9323.777   0.043       09323.777   0.043       010664.71   0.043       0
#XS Ineff= 2 , 0
       0                               0
Bank Sta=9323.777,10664.71
Exp/Cntr=0.3,0.1

Type RM Length L Ch R = 1 ,13748.33,246.501300,246.501300,246.501300
XS GIS Cut Line= 6
834356.789965411850332.851611265834630.312024746850320.685857436
834886.474503279850286.386643599835083.184581525850245.951772511
835504.174106127850145.758491883835983.046265218850054.128772523
#Sta/Elev= 30
9193.97254.495369252.19554.579959432.44448.935719492.66941.52069 9532.89 39.5622
9633.69942.04101 9816.4937.345019836.95832.352969857.426 21.65179877.89423.61334
9959.96623.73064 9980.5617.3234210001.1616.8916510021.7617.4628110032.0523.72351
10042.3526.3344210083.5528.5938910104.1534.0719610145.34 33.793610206.9343.40781
10247.9746.7992810299.2636.5923510330.0437.3351710442.5362.24849 10565.1111.0904
10585.47115.451410626.16134.762810677.02154.336210707.53171.756610847.59176.6586
#Mann= 3 , 0 , 0
9193.972    0.04       09193.972    0.04       010847.59    0.04       0
#XS Ineff= 2 , 0
       0                10213.97       0
Bank Sta=9193.972,10847.59
Exp/Cntr=0.3,0.1

Type RM Length L Ch R = 1 ,13501.83,246.501200,246.501200,246.501200
XS GIS Cut Line= 6
834298.924026159850507.339674259834498.876451887850523.523574394
834719.608903376850530.798486828834976.538517112850513.796844155
835596.299348761850382.279160215836076.353803932 850301.93447117
#Sta/Elev= 30
9094.54660.390579190.93655.19253 9341.3353.893669471.42347.842669581.44446.83417
 9641.52 41.69279802.54338.481559832.95234.851759853.22528.283219883.741 22.7223
9955.33621.1071710016.7316.8774910047.5722.9194510078.4224.0924210098.9835.16511
10119.5537.7967510232.4637.94658 10292.346.3997510334.6948.8480710385.6962.45524
10446.7574.6308910497.5575.94733 10538.283.1204210568.6885.40216 10629.597.11051
10730.81132.851110781.46146.709310811.85152.729810832.11 152.15210894.18157.3877
#Mann= 3 , 0 , 0
9094.546    0.04       09094.546    0.04       010894.18    0.04       0
#XS Ineff= 2 , 0
       09746.843        10202.06       0
Bank Sta=9094.546,10894.18
Exp/Cntr=0.3,0.1

Type RM Length L Ch R = 1 ,13255.33,246.501300,246.501300,246.501300
XS GIS Cut Line= 6
834260.674651973850622.676248736834746.759828989850699.067873909
834941.987879257850716.390653738835046.514525027850719.197559367
835227.016148879850711.625642124836155.055616233850614.356817054
#Sta/Elev= 30
8981.03171.247598995.54967.755119107.02961.461639167.83654.095059218.50943.00101
9299.58543.236119481.39837.318389551.81238.497359712.16428.687059882.20926.11262
 9912.2919.722019942.37321.06067 9972.5619.013929982.64616.2412310002.8216.05142
   1002316.6399910033.0920.0598610063.35 24.537910083.4734.0574710093.5236.59877
10294.4837.2040810485.3241.7674610726.5840.7764910756.7645.8154710786.9564.87515
10797.0167.5294910817.1367.5853210827.1970.0217710847.3268.4926110887.6271.82821
#Mann= 3 , 0 , 0
8981.031  0.0434       08981.031  0.0434       010887.62  0.0434       0
#XS Ineff= 2 , 0
       09733.523        10151.56       0
Bank Sta=8981.031,10887.62
Exp/Cntr=0.3,0.1

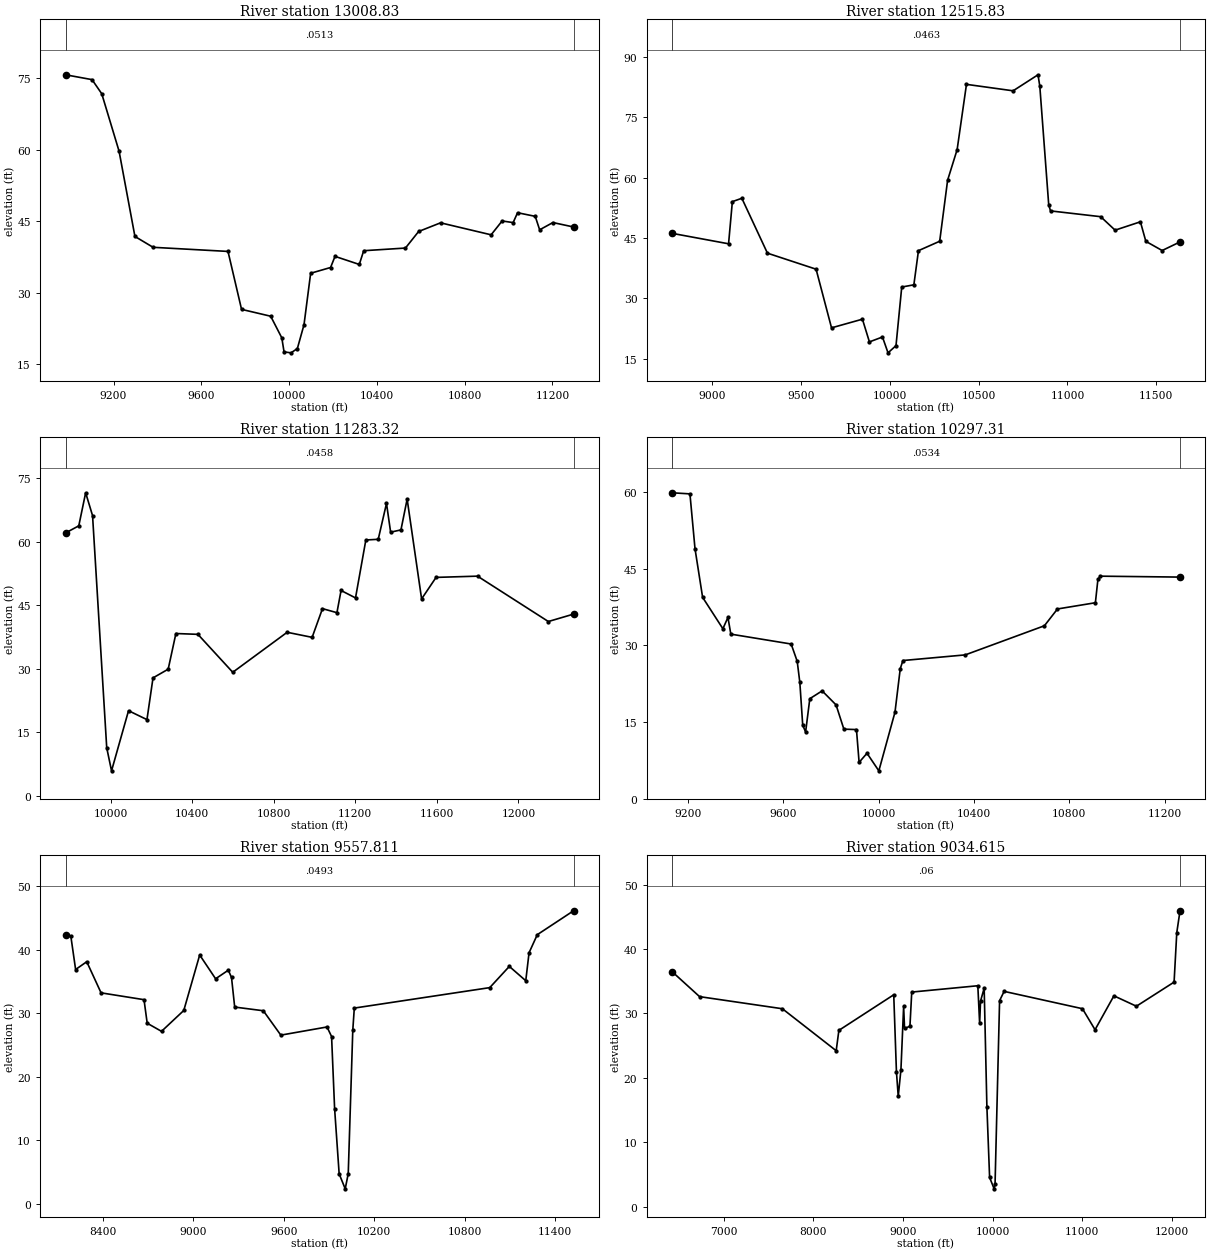
Type RM Length L Ch R = 1 ,13008.83,493.002500,493.002500,493.002500
XS GIS Cut Line= 6
834237.451594779850707.695850802835005.464801905850902.957609152
835458.335407649850977.938458333835743.620035988850997.989264595
835974.551849748850996.410064667836518.106113971850942.365665242
#Sta/Elev= 30
8981.16375.725729102.06774.707429146.34871.745869225.27759.695279297.54641.80142
9380.37839.528149721.70238.664399783.444  26.5099916.23725.068699966.96620.52513
9977.11217.5855710009.0217.3869410037.8118.2883610068.0923.2840310098.3734.08351
10189.2135.29134 10209.437.6271210320.0435.9325910340.1238.81423 10530.439.37134
10590.41 42.845310690.42 44.664910920.81 42.149710970.9645.0559711021.2244.71199
11041.3546.7848111121.8846.0240711142.01 43.198811202.4344.7232611296.48 43.7921
#Mann= 3 , 0 , 0
8981.163  0.0513       08981.163  0.0513       011296.48  0.0513       0
#XS Ineff= 2 , 0
       09792.833        10194.69       0
Bank Sta=8981.163,11296.48
Exp/Cntr=0.3,0.1

Type RM Length L Ch R = 1 ,12515.83,1232.506300,1232.506300,1232.506300
XS GIS Cut Line= 6
834010.007080385850811.792258081834647.876703476851052.336751355
835180.366523485851515.314376069835419.608551268851631.887985143
835901.756638182851649.113231399836603.110276026851530.609249202
#Sta/Elev= 30
8775.57746.146429093.91543.543369115.26354.024819168.63254.856129312.59441.21308
9586.26537.228349673.094 22.65049846.92424.804059886.25319.157219959.71520.37889
9990.90216.4384510035.7818.2225810068.0632.7927210136.2833.3447410162.1441.83457
10281.5344.1737910326.1559.3564410379.6966.9507410432.1983.1715510694.5981.56753
10834.6985.5522710844.7182.7197910894.8753.24002 10904.951.7177211187.2650.27942
11268.2346.9292811410.6549.0079411441.1944.1525411532.9541.8707211633.4544.00672
#Mann= 3 , 0 , 0
8775.577  0.0463       08775.577  0.0463       011633.45  0.0463       0
#XS Ineff= 2 , 0
       09757.134                       0
Bank Sta=8775.577,11633.45
Exp/Cntr=0.3,0.1

Type RM Length L Ch R = 1 ,11283.32,986.005000,986.005000,986.005000
XS GIS Cut Line= 6
  834236.2582059852436.279744287834573.868729244852239.792426941
834866.435412861852026.930259648835079.997194962851929.034324758
836140.898263372851736.533397258 836555.57833115851646.830328829
#Sta/Elev= 30
9779.15362.09152 9844.2563.774789877.93671.584889911.82366.18798 9981.3111.35062
10004.915.90455810088.2720.1114410178.6218.0042510208.33 27.861910282.7329.91465
10320.5938.3418410428.5738.1441710599.4629.1841210866.2138.6319410988.7437.43622
11039.4444.2181811110.3443.26424 11130.648.50629 11201.5  46.75111252.1560.43387
11312.9260.5973111353.4369.0766511373.6962.2794511424.3362.8166311454.7270.08465
11525.6246.5168511596.5451.5987511799.8651.8923112147.1741.1751112270.8242.92531
#Mann= 3 , 0 , 0
9779.153  0.0458       09779.153  0.0458       012270.82  0.0458       0
#XS Ineff= 2 , 0
       0                10792.52       0
Bank Sta=9779.153,12270.82
Exp/Cntr=0.3,0.1

Type RM Length L Ch R = 1 ,10297.31,739.503800,739.503800,739.503800
XS GIS Cut Line= 6
834524.076135576852959.101007447834909.235112833852819.649691684
835041.757771932852629.966736825 835141.76887587852548.586099284
835773.642461198852237.535608106 836393.39113461852023.960711285
#Sta/Elev= 30
 9132.7259.879969208.14959.66554 9229.4248.917579261.32539.402859346.40833.25548
9367.67835.465299379.75932.19529 9632.9630.260759658.36626.874489669.37522.73674
9681.51414.356229693.64913.02857 9711.2919.554549762.994 21.08289821.434 18.3378
9854.20713.588619907.06613.50457 9918.177.0830139951.2998.864776   100015.422482
10068.7616.9094710090.8525.4322410102.1727.0267310363.5728.1295610695.9633.83695
10750.7637.1259410909.8738.3449110920.4542.9020310931.0343.5482511265.08 43.3667
#Mann= 3 , 0 , 0
 9132.72  0.0534       0 9132.72  0.0534       011265.08  0.0534       0
#XS Ineff= 2 , 0
       0                10213.86       0
Bank Sta=9132.72,11265.08
Exp/Cntr=0.3,0.1

Type RM Length L Ch R = 1 ,9557.811,523.195200,523.195200,523.195200
XS GIS Cut Line= 6
833601.462940563852760.910587244835007.646290992853236.472901155
835731.732686161853140.993755171835925.063798406853098.850889469
836277.955536996 852979.04028772836814.297943427852744.784496781
#Sta/Elev= 30
8151.71742.36129 8187.1242.126028218.78936.882628292.68438.106078387.69133.21188
8672.714  32.1388693.82728.435628788.83427.159448936.62430.442519042.18839.16579
9147.75235.425099232.20336.775389253.31635.633449274.42830.976489464.44430.39755
9580.56426.563059887.17627.846799917.37426.342139937.50715.000899967.6674.752625
10007.862.39355510027.964.78580610058.1127.3284110068.1630.8171710967.0534.03302
 11096.9 37.3712   1120635.1205611227.8439.5147911282.4342.3574511523.1146.11716
#Mann= 3 , 0 , 0
8151.717  0.0493       08151.717  0.0493       011523.11  0.0493       0
#XS Ineff= 2 , 0
       09817.015         10221.5       0
Bank Sta=8151.717,11523.11
Exp/Cntr=0.3,0.1

Type RM Length L Ch R = 1 ,9034.615,218.007600,218.007600,218.007600
XS GIS Cut Line= 6
831859.074035853 853772.36983487832710.819103122853868.893724889
 833866.53875187853880.013756633835626.687829792853664.756938457
836387.672708482853477.765417486837481.108334571853426.776191399
#Sta/Elev= 30
6424.85336.500416732.73732.60574 7656.2530.726748256.27724.215258286.27827.37349
8898.09532.893728928.213 20.94898948.29217.13054 8978.4121.275929008.52931.09893
9018.56827.677259078.80528.009019098.88433.313489835.82334.296739856.05128.45795
9866.16531.910379906.62133.920729936.96315.521059967.3054.54674710017.882.785869
10027.99 3.5032510078.5631.9798810129.1333.4218711002.7230.7332611143.1127.47076
11353.6932.7327811604.3931.1180112024.6734.8587712054.6742.5323512090.7845.92669
#Mann= 3 , 0 , 0
6424.853    0.06       06424.853    0.06       012090.78    0.06       0
#XS Ineff= 2 , 0
       09853.822        10117.35       0
Bank Sta=6424.853,12090.78
Exp/Cntr=0.3,0.1