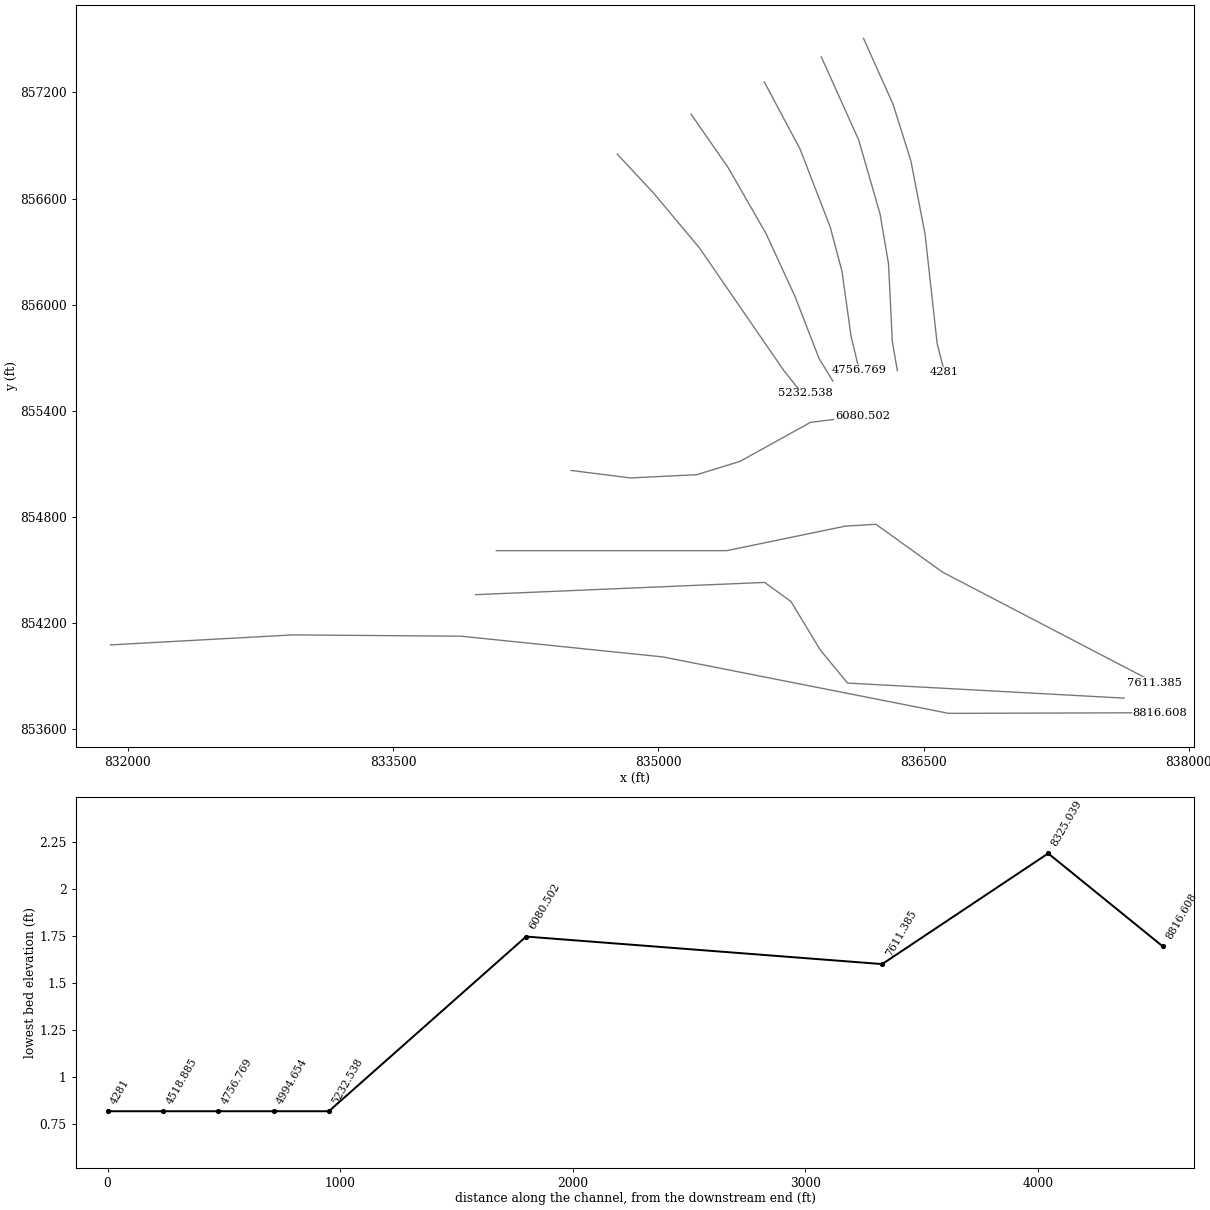
HEC-RAS study 18446_ras.prj: 18446

--- 18446_ras.g01 (geometry) --- (continued)

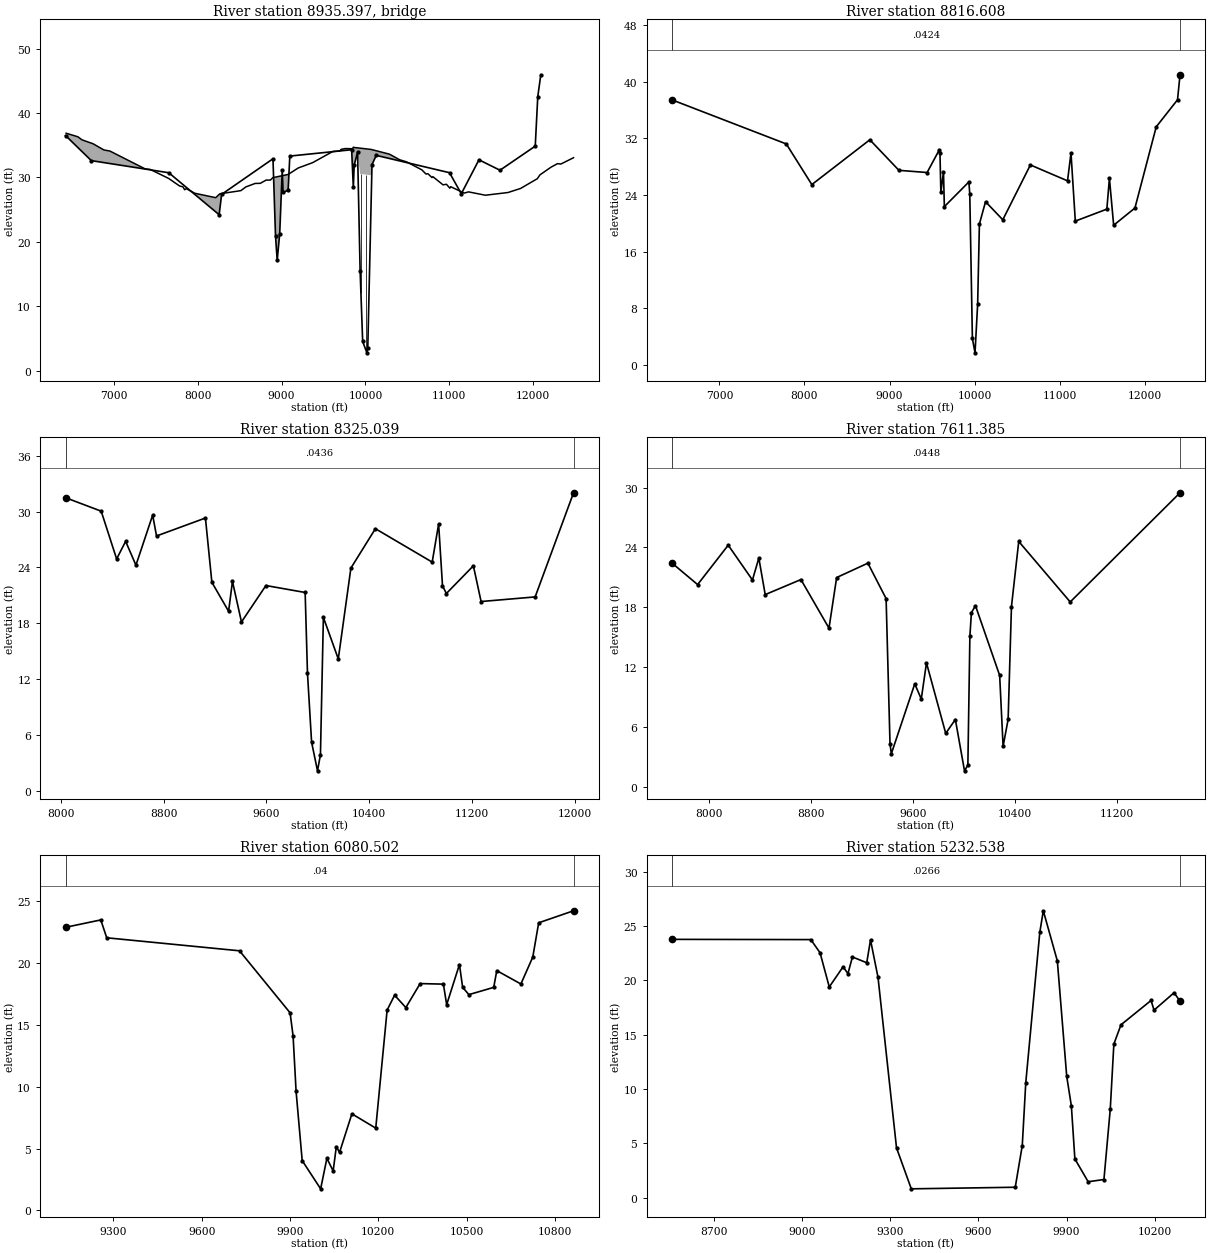
Type RM Length L Ch R = 3 ,8935.397,,,
BEGIN DESCRIPTION:
END DESCRIPTION:
Bridge Culvert--1,0,-1,-1, 0
Deck Dist Width WeirC Skew NumUp NumDn MinLoCord MaxHiCord MaxSubmerge Is_Ogee
61.503800,95.000000,2.6,0, 60, 60, , , 0.95, 0, 0,0,,
 6432.42 6572.06 6622.23 6752.66 6883.10 6953.34 7374.75 7434.95 7655.01 7785.01
 7825.01 7845.01 7865.01 7965.01 8215.01 8265.01 8515.02 8575.25 8685.97 8746.36
 8816.82 8867.15 8897.34 9078.52 9199.31 9370.43 9612.00 9692.68 9711.66 9759.59
 9846.05 9856.28 9885.69 9885.69 9886.9510069.6910069.6910286.8210408.4310490.14
10672.3710722.9910743.2410793.8610803.9810925.4710965.9711006.4611016.5911178.57
11229.1911429.8611699.8811849.9012049.9112079.9112209.9312289.9312329.9412481.19
   36.86   36.31   35.83   35.23   34.26   34.10   31.32   31.24   29.84   28.67
   28.54   28.09   28.26   27.55   26.86   27.46   27.95   28.53   29.07   29.08
   29.59   29.59   29.97   30.46   31.47   32.29   34.03   34.10   34.36   34.48
   34.45   34.69   34.60   34.60   34.62   34.34   34.34   33.61   32.74   32.42
   31.18   30.52   30.59   29.98   30.12   28.85   28.94   28.33   28.56   27.57
   27.76   27.24   27.66   28.29   29.81   30.39   31.57   32.14   32.08   33.06
 -963.14 -963.69 -964.17 -964.77 -965.74 -965.90 -968.68 -968.76 -970.16 -971.33
 -971.46 -971.91 -971.74 -972.45 -973.14 -972.54 -972.05 -971.47 -970.93 -970.92
 -970.41 -970.41 -970.03 -969.54 -968.53 -967.71 -965.97 -965.90 -965.64 -965.52
 -965.55 -965.31 -965.40   30.60   30.62   30.34 -965.66 -966.39 -967.26 -967.58
 -968.82 -969.48 -969.41 -970.02 -969.88 -971.15 -971.06 -971.67 -971.44 -972.43
 -972.24 -972.76 -972.34 -971.71 -970.19 -969.61 -968.43 -967.86 -967.92 -966.94
 6432.42 6572.06 6622.23 6752.66 6883.10 6953.34 7374.75 7434.95 7615.01 7625.01
 7655.01 7785.01 7825.01 7845.01 7865.01 7965.01 8215.01 8265.01 8515.02 8575.25
 8685.97 8746.36 8816.82 8867.15 8897.34 9078.52 9199.31 9370.43 9612.00 9692.68
 9711.66 9759.59 9846.05 9856.28 9876.73 9914.05 9914.0510098.0510098.0510286.82
10631.8810722.9910743.2410793.8610803.9810925.4710965.9711006.4611016.5911178.57
11229.1911429.8611699.8811849.9012049.9112079.9112209.9312289.9312329.9412481.19
   36.86   36.31   35.83   35.23   34.26   34.10   31.32   31.24   30.10   29.85
   29.84   28.67   28.54   28.09   28.26   27.55   26.86   27.46   27.95   28.53
   29.07   29.08   29.59   29.59   29.97   30.46   31.47   32.29   34.03   34.10
   34.36   34.48   34.45   34.69   34.49   34.58   34.58   34.30   34.30   33.61
   31.49   30.52   30.59   29.98   30.12   28.85   28.94   28.33   28.56   27.57
   27.76   27.24   27.66   28.29   29.81   30.39   31.57   32.14   32.08   33.06
 -963.14 -963.69 -964.17 -964.77 -965.74 -965.90 -968.68 -968.76 -969.90 -970.15
 -970.16 -971.33 -971.46 -971.91 -971.74 -972.45 -973.14 -972.54 -972.05 -971.47
 -970.93 -970.92 -970.41 -970.41 -970.03 -969.54 -968.53 -967.71 -965.97 -965.90
 -965.64 -965.52 -965.55 -965.31 -965.51 -965.42   30.58   30.30 -965.70 -966.39
 -968.51 -969.48 -969.41 -970.02 -969.88 -971.15 -971.06 -971.67 -971.44 -972.43
 -972.24 -972.76 -972.34 -971.71 -970.19 -969.61 -968.43 -967.86 -967.92 -966.94
Pier Skew, UpSta & Num, DnSta & Num=  ,9946.36, 2 ,9974.72, 2 , 0 , 0 , 0 ,,
    4.00    4.00
 -965.48   34.52
    4.00    4.00
 -965.53   34.47
Pier Skew, UpSta & Num, DnSta & Num=  ,10009.03, 2 ,10037.39, 2 , 0 , 0 , 0 ,,
    4.00    4.00
 -965.58   34.42
    4.00    4.00
 -965.62   34.38
BR Coef=-1 , 0 , 0 ,, 0 ,,,0.8,0,1,0,
WSPro=,,,, 1 ,,,, 0 ,,,, 0 ,,,,-1 ,-1 ,-1 , 0 , 0 , 0 , 0 , 0
BC Design=,, 0 ,, 0 ,,,,,,

Type RM Length L Ch R = 1 ,8816.608,491.569000,491.569000,491.569000
XS GIS Cut Line= 6
831902.509302527 854076.41670154832935.513253301854133.071397215
833885.423650414854125.517437771835026.071522921854008.431066781
836642.618838906853689.276281253837834.255937457853693.053260937
#Sta/Elev= 30
6442.21737.45114 7786.2731.21808 8086.2825.475878768.33731.808799110.38627.48936
9441.80527.180239582.60330.333089592.90229.877249603.20224.376349634.09927.25642
9644.39922.360749932.77925.852169943.07824.146789973.9763.72645910004.87 1.69704
10035.778.58902110056.3719.8986710128.4223.0593410331.2220.5009610655.7528.25125
11092.4726.0033311133.0929.9337511183.8720.3139611554.6822.00658 11584.726.35675
11634.7319.7286311884.9122.1664212135.1833.6403812385.4537.4596212414.7440.99348
#Mann= 3 , 0 , 0
6442.217  0.0424       06442.217  0.0424       012414.74  0.0424       0
#XS Ineff= 2 , 0
       09873.054        10136.82       0
Bank Sta=6442.217,12414.74
Exp/Cntr=0.3,0.1

Type RM Length L Ch R = 1 ,8325.039,713.653900,713.653900,713.653900
XS GIS Cut Line= 6
833967.722333692854360.540179486835600.786344339854429.692727185
835750.024208847854321.769072619835914.607499892854049.213574795
836069.527949616853860.678321764837633.384141058853775.511489332
#Sta/Elev= 30
 8037.6931.487788315.21630.040278435.32324.916078505.386 26.80598585.458 24.2459
8715.57429.618088745.60127.379339125.94229.306599175.98722.410629306.10319.30389
 9336.1322.510339406.19318.155729596.363 22.06479901.39121.319749919.59612.64879
9951.4845.2749389997.5132.18985110020.393.92051710043.2618.6499110159.1414.19243
 10257.2 23.935810447.7928.1603710889.4324.5767210939.4828.6640110969.5122.05852
10999.5321.2074411209.7224.1787811269.7720.3496811690.1520.84436 11988.832.01355
#Mann= 3 , 0 , 0
 8037.69  0.0436       0 8037.69  0.0436       0 11988.8  0.0436       0
#XS Ineff= 2 , 0
       09812.467        10226.96       0
Bank Sta=8037.69,11988.8
Exp/Cntr=0.3,0.1

Type RM Length L Ch R = 1 ,7611.385,1530.883200,1530.883200,1530.883200
XS GIS Cut Line= 6
834084.025095668854609.292407021835386.807779551854609.292407021
836058.822230611854748.180120576836230.413614112854758.338974143
836606.391162603854488.127798576 837807.08849892853862.363668248
#Sta/Elev= 30
7710.24422.430647911.21920.272298151.21924.222238341.21920.730148391.21922.93012
8441.219 19.26758721.21920.775838941.21915.904559001.21920.978639246.04222.41907
9389.00118.867059419.6354.3174599429.8463.312877 9613.6510.320869664.7078.801361
9705.49112.420569856.3915.3574429931.9996.74621210003.631.60186410030.04 2.17769
10045.7815.09121 10057.8 17.454710089.5618.1594210279.22 11.167910306.224.060686
10345.596.75222210371.7518.0679810428.81  24.59510832.3518.5305311693.1829.47449
#Mann= 3 , 0 , 0
7710.244  0.0448       07710.244  0.0448       011693.18  0.0448       0
#XS Ineff= 2 , 0
       09725.662        10168.04       0
Bank Sta=7710.244,11693.18
Exp/Cntr=0.3,0.1

Type RM Length L Ch R = 1 ,6080.502,847.963200,847.963200,847.963200
XS GIS Cut Line= 6
834506.737704254855062.835711757834842.246789009855020.340710093
835217.853670449855038.914921839 835462.39761446855114.314098404
835860.344174082855334.623350423836153.393983229 855371.18477765
#Sta/Elev= 30
9137.03322.908939256.95623.508399277.12622.062029728.44221.008889900.31215.99139
9910.50914.123479920.7489.6294179941.4544.03344710004.171.74806410025.434.219589
10046.693.19486110057.515.16619710068.354.69017910110.397.81728610191.466.659991
10230.13 16.213210255.56 17.4162 10293.716.4158110342.37 18.3572 10421.418.31259
10432.4816.6526710475.9519.8986610486.7418.0576610507.98 17.462710592.4218.05011
10602.8119.4051910684.7418.3238610725.1620.5009110745.2323.2755410863.73 24.2478
#Mann= 3 , 0 , 0
9137.033    0.04       09137.033    0.04       010863.73    0.04       0
#XS Ineff= 2 , 0
       0                               0
Bank Sta=9137.033,10863.73
Exp/Cntr=0.3,0.1

Type RM Length L Ch R = 1 ,5232.538,237.884600,237.884600,237.884600
XS GIS Cut Line= 6
834767.589748773856851.558249141834974.031226113856629.992997707
835232.825631656856320.472407946 835709.64812087855627.577806883
835784.426923605855533.657154008835832.872551166855499.988849341
#Sta/Elev= 30
8558.32723.772879030.55923.750669061.849 22.53549093.13819.394819140.07321.24689
9156.63520.62159  9171.922.153039220.56121.620379233.34623.722259258.91720.27152
9321.8114.5883269372.0450.8202089725.5030.9669689749.3524.8027849761.27610.58077
9808.97424.425799820.898 26.40269868.59621.791899900.51411.168419916.293 8.44707
9928.2183.5726919973.4621.47162510027.071.67858310048.658.19072110060.7714.13966
   1008515.91275 10187.218.1508110197.4617.2607810265.4718.8609510285.7118.09259
#Mann= 3 , 0 , 0
8558.327  0.0266       08558.327  0.0266       010285.71  0.0266       0
#XS Ineff= 2 , 0
       0                               0
Bank Sta=8558.327,10285.71
Exp/Cntr=0.3,0.1

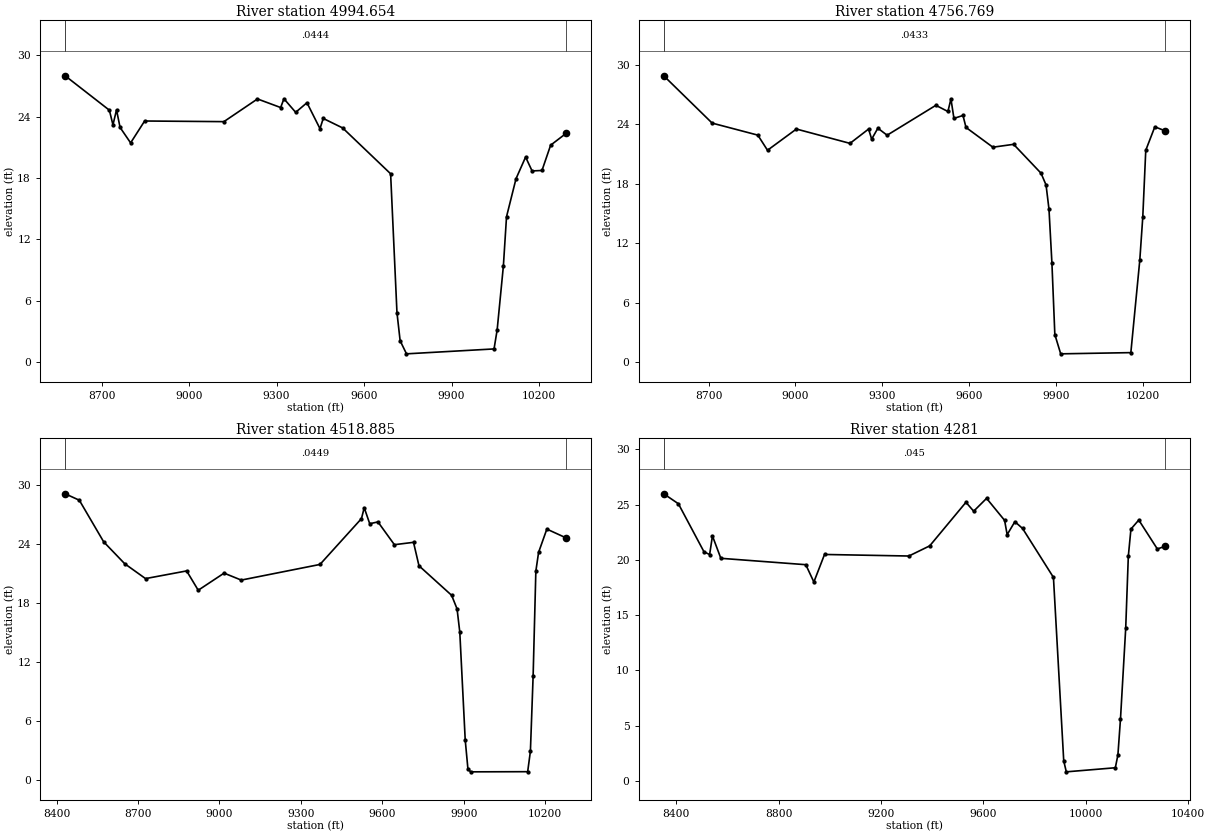
Type RM Length L Ch R = 1 ,4994.654,237.884600,237.884600,237.884600
XS GIS Cut Line= 6
835184.714518759 857077.81766479 835392.93116398856777.732703725
835608.022243753856403.992312663 835772.24214328 856047.65922432
835908.364511701855696.761347468835986.898973765855567.858343417
#Sta/Elev= 30
8575.32727.984758726.967 24.62198739.20523.189358751.44324.650888763.68122.93521
8799.78921.428798847.83523.566969119.61723.503829234.731 25.72159314.14124.88223
9325.48525.738019365.60424.413849404.359 25.35099448.99722.818869460.15623.81637
9526.72322.888539691.15718.411699712.926 4.84244 9723.81 2.096679745.5790.820208
10045.771.29986210056.423.16244810077.739.39350810088.5414.21799 10121.117.93078
10153.9520.0450510176.1418.6886110210.0918.7337310239.7621.2043310292.5122.35146
#Mann= 3 , 0 , 0
8575.327  0.0444       08575.327  0.0444       010292.51  0.0444       0
#XS Ineff= 2 , 0
       0                               0
Bank Sta=8575.327,10292.51
Exp/Cntr=0.3,0.1

Type RM Length L Ch R = 1 ,4756.769,237.884700,237.884700,237.884700
XS GIS Cut Line= 6
835598.881827464857259.601506168835801.485281968856879.850615242
835971.720241115 856439.22242799836038.414448732856189.084901037
 836089.75019755855820.988850748836134.956581117855633.097766215
#Sta/Elev= 30
8545.48528.89568 8712.5424.116698870.11422.903698903.53521.375019003.25923.51838
9188.152  22.0719252.25823.516029262.942 22.4992 9284.3123.603169316.20122.89382
9484.39425.913219525.99225.289119536.39226.555739546.79224.593689577.99124.88718
 9588.39 23.67769681.07421.683779752.67721.974479847.24919.057549864.57117.87137
9874.67815.428699884.78410.007839894.8912.7716499915.1040.82020810157.120.942627
   1018810.2822610198.2914.6367910208.5921.3718210239.83  23.74110273.5823.35906
#Mann= 3 , 0 , 0
8545.485  0.0433       08545.485  0.0433       010273.58  0.0433       0
#XS Ineff= 2 , 0
       0                               0
Bank Sta=8545.485,10273.58
Exp/Cntr=0.3,0.1

Type RM Length L Ch R = 1 ,4518.885,237.884600,237.884600,237.884600
XS GIS Cut Line= 6
835921.376704713857401.149031477836132.955042009856930.968662547
836253.674324889 856513.04089196836301.436693747  856231.8455588
836322.815244956855794.485551473836351.410582457855626.474196719
#Sta/Elev= 30
8431.28129.131748483.51428.476028573.30924.236728650.75122.010818727.492 20.4951
8878.94321.277568921.67619.310059016.957 21.05199080.26620.343699370.33821.93674
9523.24426.603829533.39827.714639553.66526.082749583.96726.266669644.57223.94764
9715.04324.188519735.14521.800719855.48518.793049875.51717.409229885.53315.05323
9905.5524.0642089915.5531.1074479925.5540.82020810135.720.83583310145.762.916574
 10155.810.5938510165.8421.2516910175.9323.1671310206.3625.5351310277.0124.64384
#Mann= 3 , 0 , 0
8431.281  0.0449       08431.281  0.0449       010277.01  0.0449       0
#XS Ineff= 2 , 0
       0                               0
Bank Sta=8431.281,10277.01
Exp/Cntr=0.3,0.1

Type RM Length L Ch R = 1 ,    4281,0.000000,0.000000,0.000000
XS GIS Cut Line= 6
836160.095725443857505.926158223836328.155433916857130.563765155
836427.668694701856814.014034742836508.006615281856399.298537819
836576.557289375855779.336898439 836618.00083719855618.316440014
#Sta/Elev= 30
8350.913  25.9768408.17925.072888508.08120.730848530.17620.477568541.22322.16051
8574.041 20.13798905.86919.560168937.41117.994018979.03520.485929308.46720.34505
9389.92121.264189531.46325.206139561.68824.399649612.06325.561929682.40423.57274
9692.44922.278969722.58423.451469752.71922.836229873.25918.410459913.4391.811497
9923.4840.82020810114.971.18962810125.072.34773810135.185.62415210155.5313.81025
10165.7420.3211410175.9522.7818210206.5623.6005810279.0320.9858610307.46 21.2066
#Mann= 3 , 0 , 0
8350.913   0.045       08350.913   0.045       010307.46   0.045       0
#XS Ineff= 2 , 0
       0                               0
Bank Sta=8350.913,10307.46
Exp/Cntr=0.3,0.1